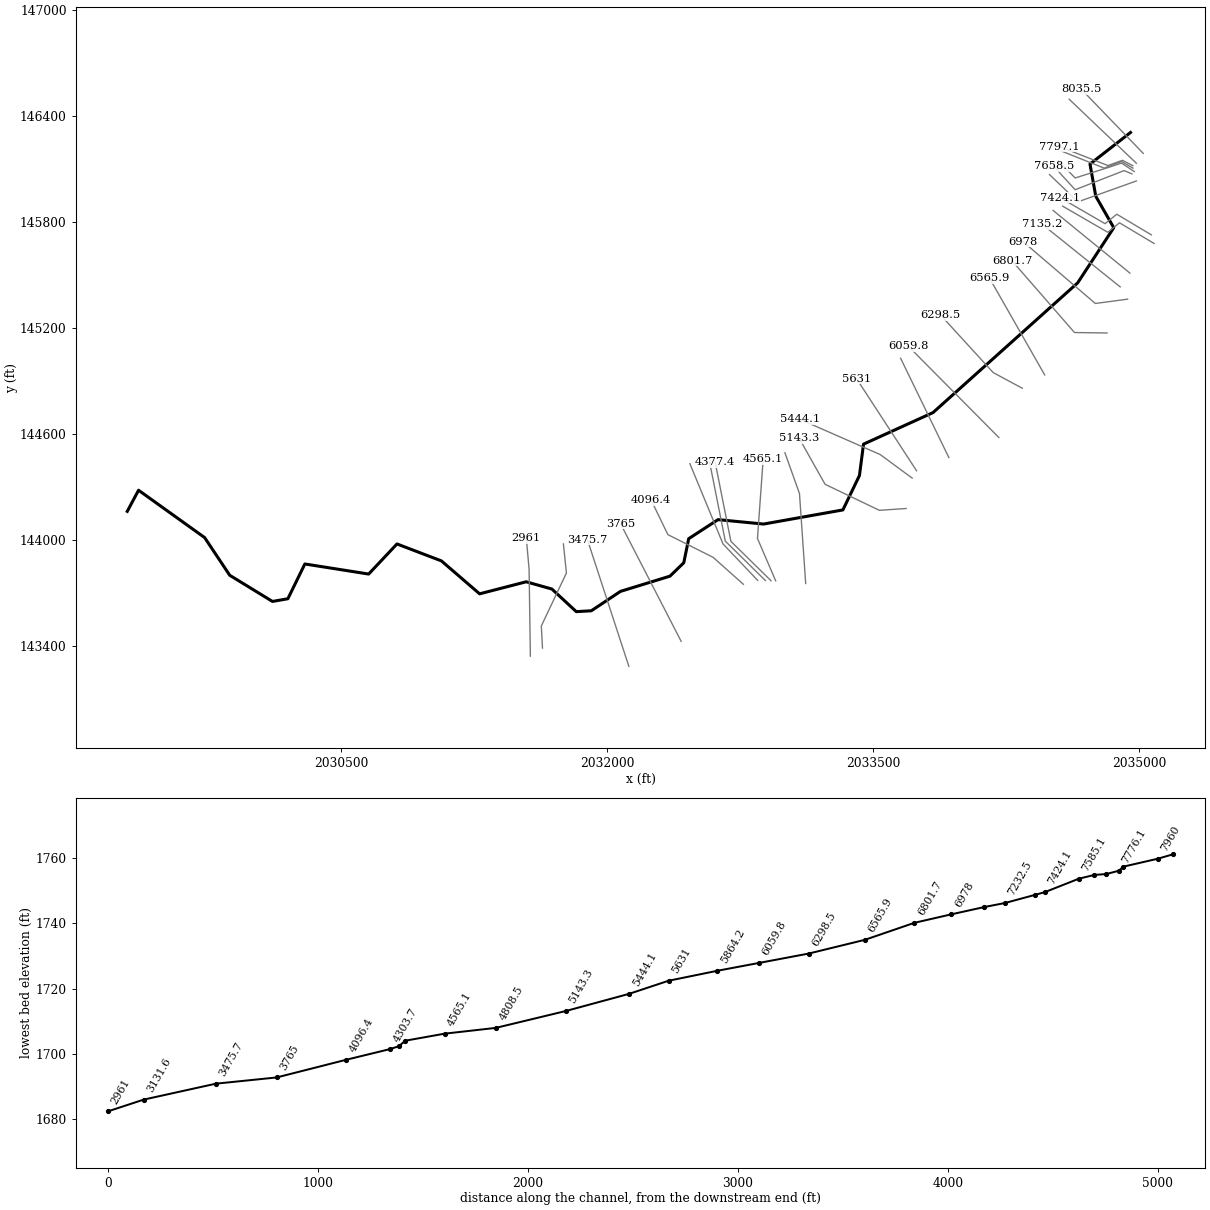
--- SCOTTBR.prj (project) ---

Proj Title=SCOTTBR
Current Plan=p01
Default Exp/Contr=0,0
English Units
Geom File=g01
Flow File=f01
Plan File=p01
BEGIN DESCRIPTION:
END DESCRIPTION:
DSS Export Rating Curves= 0
DSS Export Rating Curve Sorted= 0
DSS Export Volume Flow Curves= 0
DXF OffsetX= 0
DXF OffsetY= 0
DXF ScaleX= 0
DXF ScaleY= 0

--- SCOTTBR.p01 (plan) ---

Plan Title=Floodplain
Program Version=4.00
Geom File=g01
Flow File=f01
K Sum by GR=0
Std Step Tol=0.01
Critical Tol=0.01
Num of Std Step Trials=20
Max Error Tol=0.3
Flow Tol Ratio=0.001
Split Flow NTrial=30
Split Flow Tol=0.02
Split Flow Ratio=0.02
Log Output Level=0
Friction Slope Method=1
Unsteady Friction Slope Method=2
Unsteady Bridges Friction Slope Method=1
Global Log Level=0
CheckData=False
Run HTab=0
Run UNet=0
Run PostProcess=0
UNET Theta=0
UNET Theta Warmup=0
UNET ZTol=0
UNET ZSATol=0
UNET MxIter=0
UNET MaxInSteps=0
UNET DtIC=0
UNET DtMin=0
UNET MaxCRTS=0
UNET WFStab=0
UNET SFStab=0
UNET WFX=0
UNET SFX=0
UNET DSS MLevel=0
UNET DZMax Abort=0
UNET Convert EG Bridges=0
UNET Use Existing IB Tables=0
UNET Froude Limit=0
UNET Froude Power=0
Write IC File=0
Echo Input=False
Echo Output=False
Write Detailed=0

--- SCOTTBR.f01 (steady flow) ---

Flow Title=NFF Regression Equation
Program Version=4.10
Number of Profiles= 1
Profile Names=P100yr
River Rch & RM=SCOTTBR,Main            ,8035.5
315.2002
River Rch & RM=SCOTTBR,Main            ,7776.1
712.4007
River Rch & RM=SCOTTBR,Main            ,2656.9
774.2687
River Rch & RM=SCOTTBR,Main            ,2349.1
1010.608
Boundary for River Rch & Prof#=SCOTTBR,Main            , 1
Up Type= 0
Dn Type= 1
Dn Known WS=1643.424
DSS Import GetInterval= 0
DSS Import GetPeak= 0
DSS Import FillOption= 0

--- SCOTTBR.g01 (geometry) ---

Geom Title=USGS 10m DEM
Program Version=4.10

River Reach=SCOTTBR         ,Main
Reach XY= 30
     2034949.723      146305.122      2034721.25       146126.65
     2034753.889      145944.706     2034855.278      145766.928
     2034651.806      145455.122     2033836.094      144721.789
     2033444.167      144543.404     2033421.164      144365.886
     2033327.819      144171.529     2032880.597      144091.668
     2032623.652      144116.668     2032458.374      144009.029
     2032430.596      143872.917     2032352.819      143797.223
     2032073.652      143711.112     2031909.069       143601.39
     2031824.346      143596.528     2031686.846      143724.306
     2031541.707      143765.278     2031279.208      143697.223
      2031063.93      143883.334     2030813.235      143979.167
     2030653.513      143809.029     2030293.791      143865.973
     2030197.958      143669.445     2030111.152      143654.167
      2029870.18      143802.084     2029728.513      144015.279
     2029355.915      144282.813     2029292.255      144163.444

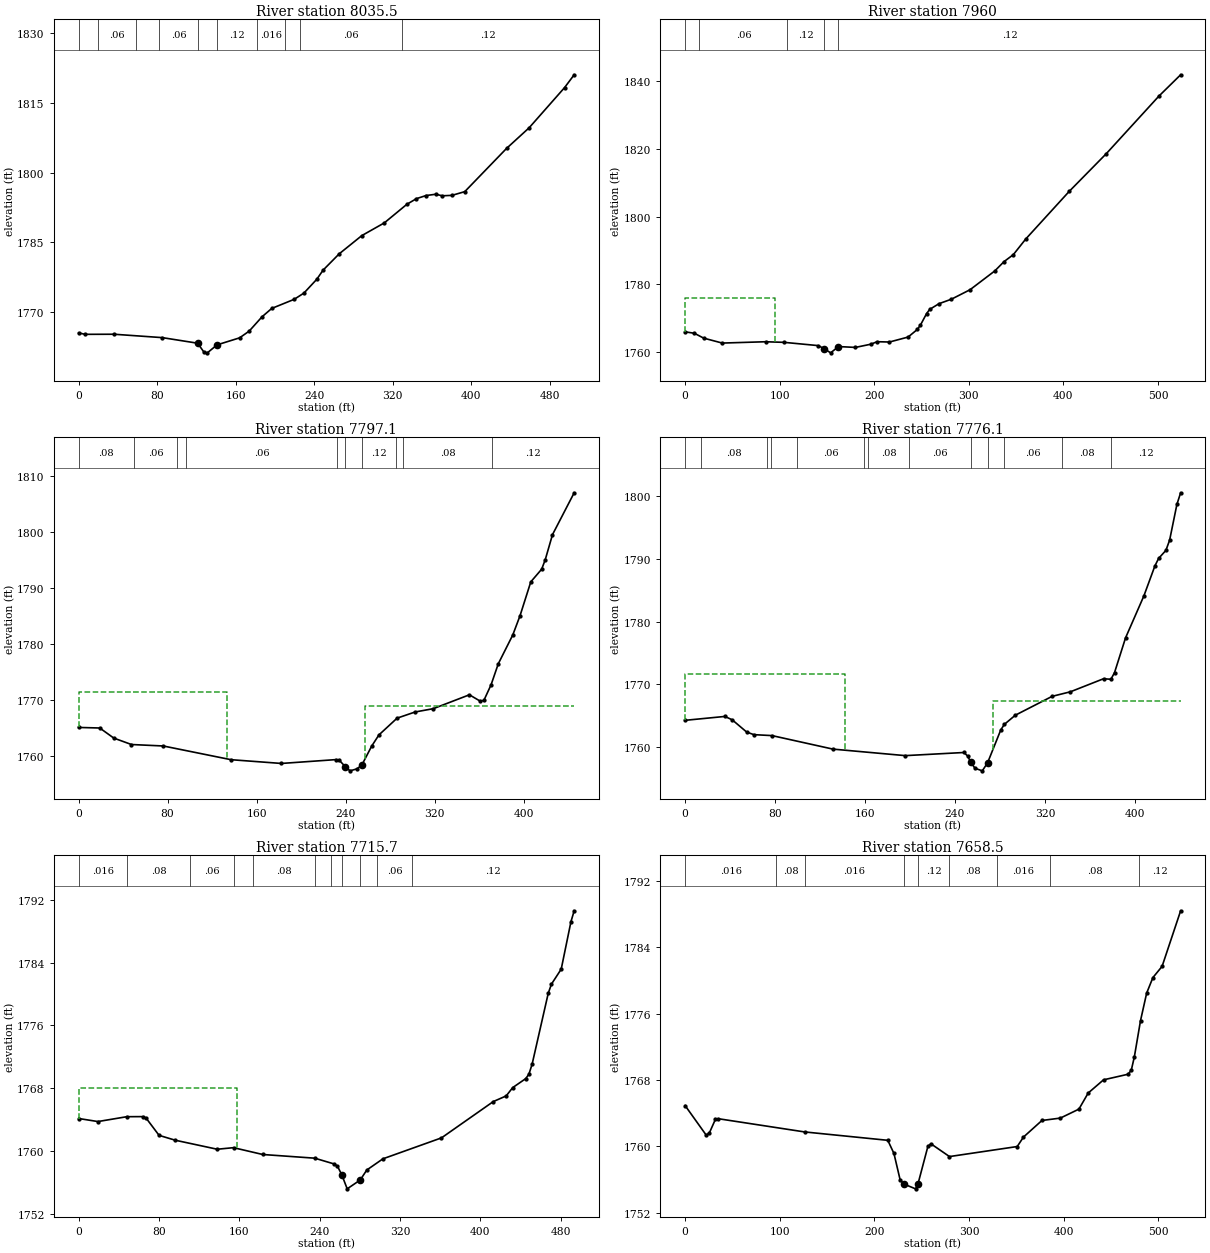
Type RM Length L Ch R = 1 ,8035.5  ,74.6,75.5,76.5
XS GIS Cut Line= 2
     2035021.708      146186.966     2034671.366      146550.688
#Sta/Elev= 30
       0 1765.53     6.6 1765.22    36.1 1765.24    85.3 1764.51   121.3 1763.31
   127.9 1761.33   131.2 1761.24     141 1762.95     164 1764.46   173.8 1765.91
   186.9 1768.99   196.8 1770.79   219.7 1772.75   229.6 1774.09   242.7 1777.06
   249.2 1779.04   265.6 1782.54   288.6 1786.45   311.5 1789.18   334.5 1793.18
   344.3  1794.4   354.2 1795.07     364 1795.34   370.6 1795.01   380.4  1795.1
   393.5  1795.9   436.1  1805.2   459.1 1809.63   495.2 1818.27     505 1821.03
#Mann= 10 ,-1 , 0
       0    .016       0      20     .06       0    58.4     .08       0
    82.4     .06       0   121.3    .045       0     141     .12       0
   181.4    .016       0   210.2     .12       0   225.4     .06       0
   329.9     .12       0
Bank Sta=121.3,141
XS Rating Curve= 0 ,0
Exp/Cntr=0.3,0.1

Type RM Length L Ch R = 1 ,7960    ,153.7,162.9,171.5
XS GIS Cut Line= 2
     2034982.645       146131.41     2034603.826       146493.39
#Sta/Elev= 30
       0 1766.02     9.8  1765.6    19.6 1764.17    39.3 1762.71    85.1  1763.1
   104.8 1762.92   140.8 1761.96   147.2 1761.03   153.9 1759.83   162.2 1761.68
   180.1 1761.43   196.5 1762.38     203 1763.11   216.1 1763.02   235.8 1764.48
   245.6 1766.73   248.9 1768.03   255.4 1771.42   258.7 1772.65   268.5 1774.32
   281.6 1775.64   301.3 1778.43   327.5 1783.98   337.3 1786.73   347.1 1788.78
   360.2 1793.38   406.1  1807.4   445.4 1818.54     501  1835.5     524 1841.79
#Mann= 5 , 0 , 0
       0    .016       0    15.1     .06       0   108.2     .12       0
   147.2    .045       0   162.2     .12       0
#XS Ineff= 2 , 0
           95.31    1776
Permanent Ineff=
       F       F
Bank Sta=147.2,162.2
XS Rating Curve= 0 ,0
Exp/Cntr=0.3,0.1

Type RM Length L Ch R = 1 ,7797.1  ,21.7,21,20.7
XS GIS Cut Line= 4
     2034962.854      146117.521     2034903.826      146148.077
     2034822.576      146118.216     2034550.354       146225.16
#Sta/Elev= 30
       0 1765.17      19 1765.07    31.6 1763.27    47.5 1762.12    76.1 1761.86
     137 1759.41   182.3 1758.74     231 1759.42   234.3 1759.32   239.8 1758.15
     244 1757.42   250.5 1757.79   254.8 1758.53   263.5 1761.85     270 1763.84
   286.3 1766.83   302.5 1767.93   318.8 1768.52   351.3    1771     361 1769.87
   364.3 1769.99   370.8 1772.79   377.3 1776.55   390.3 1781.68   396.8 1785.11
   406.5 1791.17   416.3 1793.44   419.5 1795.13     426  1799.6   445.5 1807.08
#Mann= 10 ,-1 , 0
       0     .08       0    49.8     .06       0    88.7     .08       0
    96.2     .06       0   232.4     .12       0   239.8    .045       0
   254.8     .12       0   285.4     .06       0   291.7     .08       0
   371.6     .12       0
#XS Ineff= 2 , 0
          133.41 1771.43  257.21         1768.93
Permanent Ineff=
       F       F
Bank Sta=239.8,254.8
XS Rating Curve= 0 ,0
Exp/Cntr=0.3,0.1

Type RM Length L Ch R = 1 ,7776.1  ,43.5,60.4,76.5
XS GIS Cut Line= 4
     2034963.548      146103.633     2034899.659      146141.133
     2034801.222      146103.633     2034558.687      146200.855
#Sta/Elev= 30
       0 1764.24    35.4 1764.86    41.9 1764.32    54.8 1762.36    61.2 1761.95
    77.3  1761.8   131.5 1759.64   195.8  1758.6     248  1759.1   251.3 1758.53
     254 1757.57   257.8 1756.58   264.3 1756.17     269 1757.45   280.7 1762.69
   283.9 1763.59   293.7 1765.06   326.4 1768.07   342.7  1768.8   372.1 1770.88
   378.7  1770.8   381.9 1771.86   391.7 1777.41     408 1784.11   417.8  1788.9
   421.1  1790.1   427.6 1791.39   430.9 1793.02   437.4 1798.75   440.7 1800.59
#Mann= 13 ,-1 , 0
       0    .016       0    14.3     .08       0    72.7     .06       0
    76.1     .08       0    99.5     .06       0   159.1    .016       0
   162.7     .08       0   198.9     .06       0     254    .045       0
     269     .12       0   283.9     .06       0   334.9     .08       0
     379     .12       0
#XS Ineff= 2 , 0
          141.89 1771.71   273.6         1767.29
Permanent Ineff=
       F       F
Bank Sta=254,269
XS Rating Curve= 0 ,0
Exp/Cntr=0.3,0.1

Type RM Length L Ch R = 1 ,7715.7  ,56.7,57.2,58
XS GIS Cut Line= 5
     2034971.187      146084.188     2034899.312      146132.278
        2034829.      146108.841      2034637.68      146048.077
     2034545.015      146142.131
#Sta/Elev= 30
       0 1764.12    19.2 1763.73      48 1764.35    64.1 1764.36    67.3 1764.15
    80.1 1761.97    96.2 1761.35     138  1760.2   154.2  1760.4   183.3 1759.53
   235.1 1759.06   254.5 1758.32   257.7 1758.04     262 1756.95   267.4 1755.15
   280.4 1756.28   286.9 1757.55     303 1758.98   361.3 1761.65   412.9 1766.28
   425.7    1767   432.2 1768.06   445.1  1769.2   448.3 1769.76   451.5 1771.03
   467.6  1780.1   470.8 1781.26   480.5 1783.17   490.2 1789.22   493.4 1790.61
#Mann= 11 ,-1 , 0
       0    .016       0      48     .08       0   111.1     .06       0
   154.2    .016       0   173.3     .08       0   235.3     .06       0
   251.5    .016       0     262    .045       0   280.4     .08       0
   297.3     .06       0   331.9     .12       0
#XS Ineff= 2 , 0
          157.43 1768.05
Permanent Ineff=
       F       F
Bank Sta=262,280.4
XS Rating Curve= 0 ,0
Exp/Cntr=0.3,0.1

Type RM Length L Ch R = 1 ,7658.5  ,74,73.4,72.7
XS GIS Cut Line= 4
     2034957.993      146070.994     2034913.722      146089.744
      2034637.68      145981.671     2034516.803      146113.919
#Sta/Elev= 30
       0 1764.91    22.4 1761.33    25.6  1761.6      32 1763.24    35.3 1763.32
   126.3 1761.73   214.2 1760.72   220.7 1759.14   227.2 1755.98     231 1755.46
   243.5 1754.87     246 1755.41   256.6 1759.99   259.8  1760.3   279.4 1758.76
     351 1759.97   357.6 1761.11   377.1 1763.11   396.6  1763.4   416.2 1764.48
     426 1766.42   442.2 1768.01   468.3 1768.69   471.6  1769.2   474.8 1770.79
   481.3 1775.15   487.8 1778.47   494.4 1780.34   504.1 1781.69   523.7 1788.39
#Mann= 9 ,-1 , 0
       0    .016       0    96.5     .08       0   126.3    .016       0
     231    .045       0     246     .12       0     279     .08       0
   329.4    .016       0   385.4     .08       0   480.1     .12       0
Bank Sta=231,246
XS Rating Curve= 0 ,0
Exp/Cntr=0.3,0.1

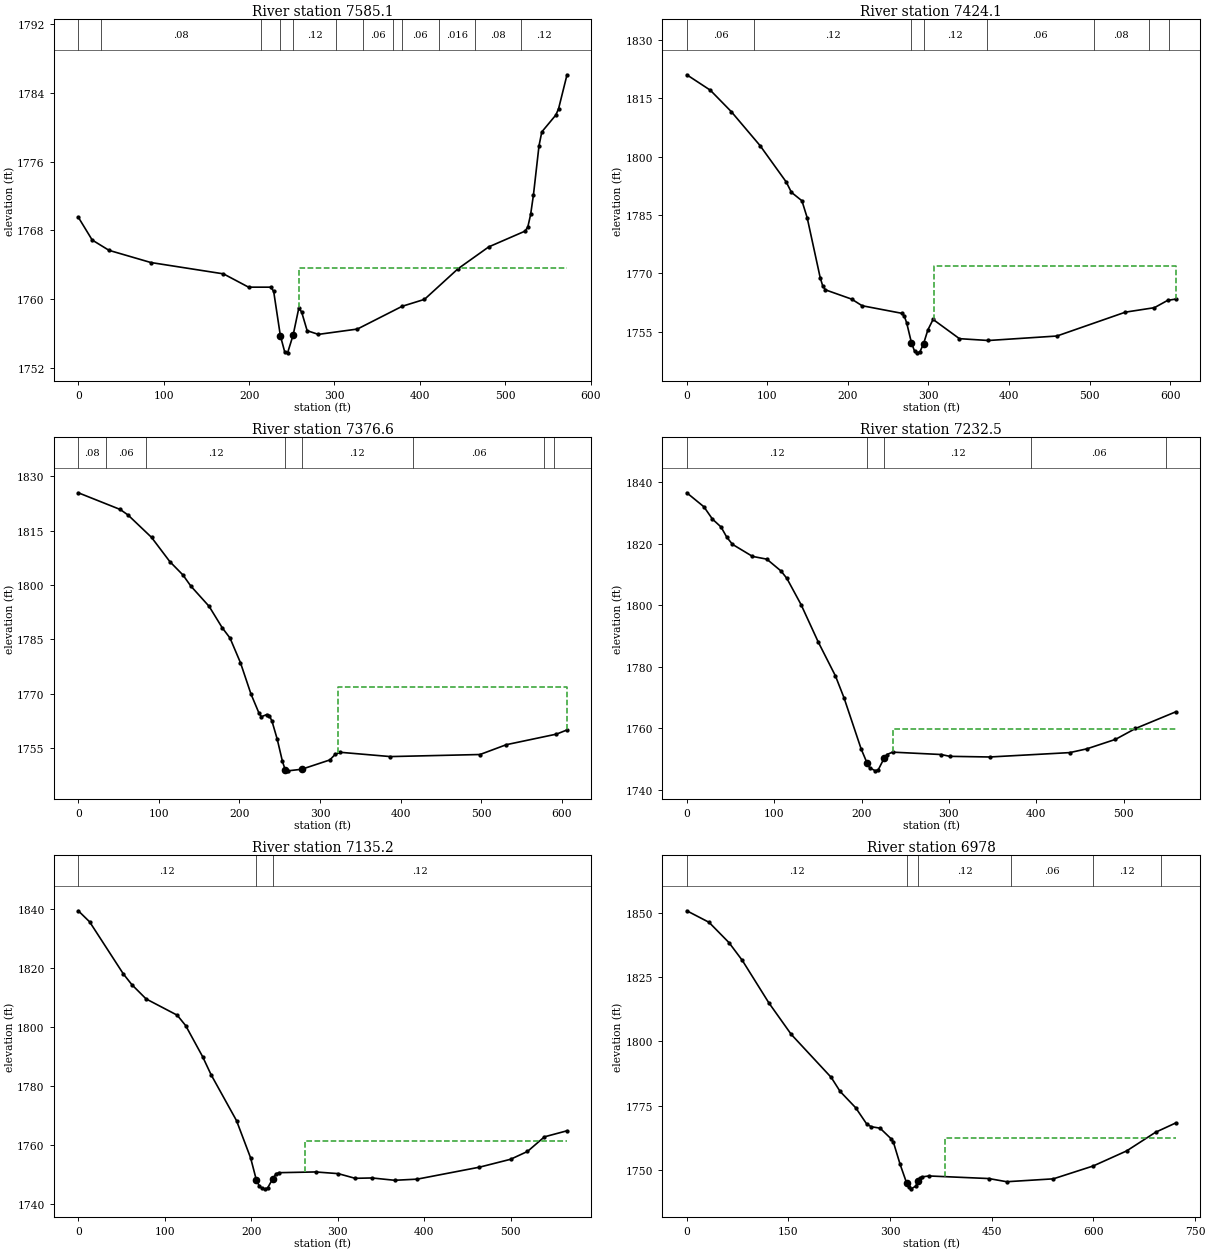
Type RM Length L Ch R = 1 ,7585.1  ,153.4,161.1,168.6
XS GIS Cut Line= 3
     2034982.732       146031.15     2034653.522      145913.181
     2034492.932      146067.261
#Sta/Elev= 30
       0 1769.52    16.3 1766.86      36 1765.66      85 1764.24     170 1762.92
   199.4 1761.37   225.5 1761.37   228.8 1760.88   236.6 1755.73   241.8  1753.8
   245.1 1753.72   251.6  1755.8   258.2 1758.92   261.5 1758.49     268  1756.3
   281.1 1755.87   326.8 1756.49   379.2 1759.14   405.4 1759.95   444.6 1763.51
   480.6 1766.06   523.2  1767.9   526.4 1768.38   529.7 1769.84     533 1772.12
   539.5 1777.84   542.8 1779.46   559.2 1781.42   562.4 1782.15   572.3 1786.11
#Mann= 12 ,-1 , 0
       0    .016       0    26.9     .08       0   214.2     .12       0
   236.6    .045       0   251.6     .12       0   301.7     .08       0
     333     .06       0     369     .08       0   379.2     .06       0
   421.9    .016       0   464.6     .08       0   518.4     .12       0
#XS Ineff= 2 , 0
                          258.45         1763.57
Permanent Ineff=
       F       F
Bank Sta=236.6,251.6
XS Rating Curve= 0 ,0
Exp/Cntr=0.3,0.1

Type RM Length L Ch R = 1 ,7424.1  ,47.4,47.5,58.7
XS GIS Cut Line= 4
     2035067.368      145726.462     2034872.316      145843.172
     2034806.343        145789.7     2034551.743        145937.4
#Sta/Elev= 30
       0 1821.04    29.2 1817.08    55.2 1811.58    90.9 1802.86   123.4 1793.51
   129.9 1790.84   142.9 1788.68   149.4 1784.35   165.6 1768.91   168.8 1766.76
   172.1  1765.8   204.6 1763.42   217.6 1761.72   266.5 1759.79   269.8 1759.16
     273 1757.26   278.9 1752.17   282.8    1750   286.1 1749.62   289.4 1749.91
   293.9 1751.96   299.2  1755.5   305.7  1758.2   338.4 1753.26   374.4 1752.79
   459.4 1753.94   544.4 1760.07   580.4 1761.22   596.8 1763.09   606.6 1763.42
#Mann= 8 ,-1 , 0
       0     .06       0    83.6     .12       0   278.9    .045       0
   293.9     .12       0   372.3     .06       0     505     .08       0
   573.3     .06       0     599    .016       0
#XS Ineff= 2 , 0
                          306.27         1771.93
Permanent Ineff=
       F       F
Bank Sta=278.9,293.9
XS Rating Curve= 0 ,0
Exp/Cntr=0.3,0.1

Type RM Length L Ch R = 1 ,7376.6  ,176.1,144.1,99.1
XS GIS Cut Line= 4
     2035082.645      145677.851     2034887.593      145794.561
     2034821.621      145741.089      2034567.02      145888.789
#Sta/Elev= 30
       0 1825.41      52 1820.81    61.7 1819.29    90.9 1813.12   113.6 1806.44
   129.9 1802.75   139.6 1799.72   162.4  1794.1   178.6 1788.22   188.3 1785.37
   201.3 1778.56   214.3 1769.96   224.1 1764.76   227.3 1763.67   233.8 1764.27
   237.1 1763.99   240.4 1762.46   246.9  1757.5   253.4 1751.36   256.7 1749.12
     260 1748.76   277.2 1749.19   312.2 1751.76   318.8 1753.29   325.3 1753.87
   387.4 1752.69   498.6 1753.26   531.3 1755.97   593.5 1758.88   606.6 1760.03
#Mann= 8 ,-1 , 0
       0     .08       0    34.3     .06       0    83.8     .12       0
   256.7    .045       0   277.2     .12       0   415.2     .06       0
   578.2     .08       0   590.9     .06       0
#XS Ineff= 2 , 0
                           322.1         1771.79
Permanent Ineff=
       F       F
Bank Sta=256.7,277.2
XS Rating Curve= 0 ,0
Exp/Cntr=0.3,0.1

Type RM Length L Ch R = 1 ,7232.5  ,97.2,97.3,97.5
XS GIS Cut Line= 2
     2034946.317      145510.403     2034513.331      145864.483
#Sta/Elev= 30
       0 1836.55    19.6    1832    29.4 1827.99    39.2 1825.44    45.8 1822.11
    52.3  1819.8    75.2 1815.89    91.6 1814.99   107.9 1811.13   114.5 1808.76
   130.8 1800.22   150.5 1788.05   170.1 1777.09   179.9 1769.99   199.5 1753.39
   206.1 1748.93   209.3 1747.23   215.9 1746.25   219.2 1746.65   225.7 1750.26
     229 1751.54   235.5 1752.32   291.1 1751.55   300.9 1750.96   346.7 1750.75
   438.3 1752.17   457.9  1753.4   490.6 1756.47   513.5    1760   559.3 1765.38
#Mann= 5 , 0 , 0
       0     .12       0   206.1    .045       0   225.7     .12       0
     394     .06       0   548.8    .016       0
#XS Ineff= 2 , 0
                           236.4         1759.88
Permanent Ineff=
       F       F
Bank Sta=206.1,225.7
XS Rating Curve= 0 ,0
Exp/Cntr=0.3,0.1

Type RM Length L Ch R = 1 ,7135.2  ,157.8,157.2,156.4
XS GIS Cut Line= 2
      2034891.63      145432.278     2034451.482      145786.358
#Sta/Elev= 30
       0 1839.35    13.1  1835.6    52.2 1817.88      62 1814.26    78.4 1809.45
   114.3 1803.94   124.1 1800.41   143.7 1789.87   153.5 1783.74   182.9 1768.16
   199.2 1755.51   205.7 1748.17     209 1746.12   212.2 1745.19   215.5 1745.03
   218.8  1745.3   224.6 1748.36   228.6 1750.13   231.8 1750.51   274.3 1750.76
   300.4 1750.19     320  1748.6   339.6 1748.72   365.7 1747.93   391.8 1748.32
   463.7 1752.38   499.6 1755.05   519.2 1757.71   538.8 1762.67   564.9 1764.72
#Mann= 3 , 0 , 0
       0     .12       0   205.7    .045       0   224.6     .12       0
#XS Ineff= 2 , 0
                          262.18         1761.19
Permanent Ineff=
       F       F
Bank Sta=205.7,224.6
XS Rating Curve= 0 ,0
Exp/Cntr=0.3,0.1

Type RM Length L Ch R = 1 ,6978    ,179.7,176.3,173
XS GIS Cut Line= 3
      2034933.32      145362.891     2034751.318      145338.624
     2034343.395      145688.546
#Sta/Elev= 30
       0 1850.71    32.8 1846.24    62.3 1838.34      82 1831.42   121.3 1814.88
   154.1 1802.74   213.1 1786.04   226.2 1780.61   249.2 1774.26   265.5 1767.94
   272.1 1766.91   285.2 1766.33   301.6 1762.18   304.9 1760.85   314.7 1752.35
   324.5 1744.96   327.8 1743.33   331.1 1742.79   337.6  1743.8   341.7 1745.71
   344.2 1746.96   347.5 1747.44   357.3 1747.79   445.8 1746.78     472 1745.55
   540.8 1746.67   599.8 1751.68     649 1757.51   691.6 1764.74   721.1 1768.32
#Mann= 6 ,-1 , 0
       0     .12       0   324.5    .045       0   341.7     .12       0
     478     .06       0   599.8     .12       0   700.4     .06       0
#XS Ineff= 2 , 0
                          381.23         1762.71
Permanent Ineff=
       F       F
Bank Sta=324.5,341.7
XS Rating Curve= 0 ,0
Exp/Cntr=0.3,0.1

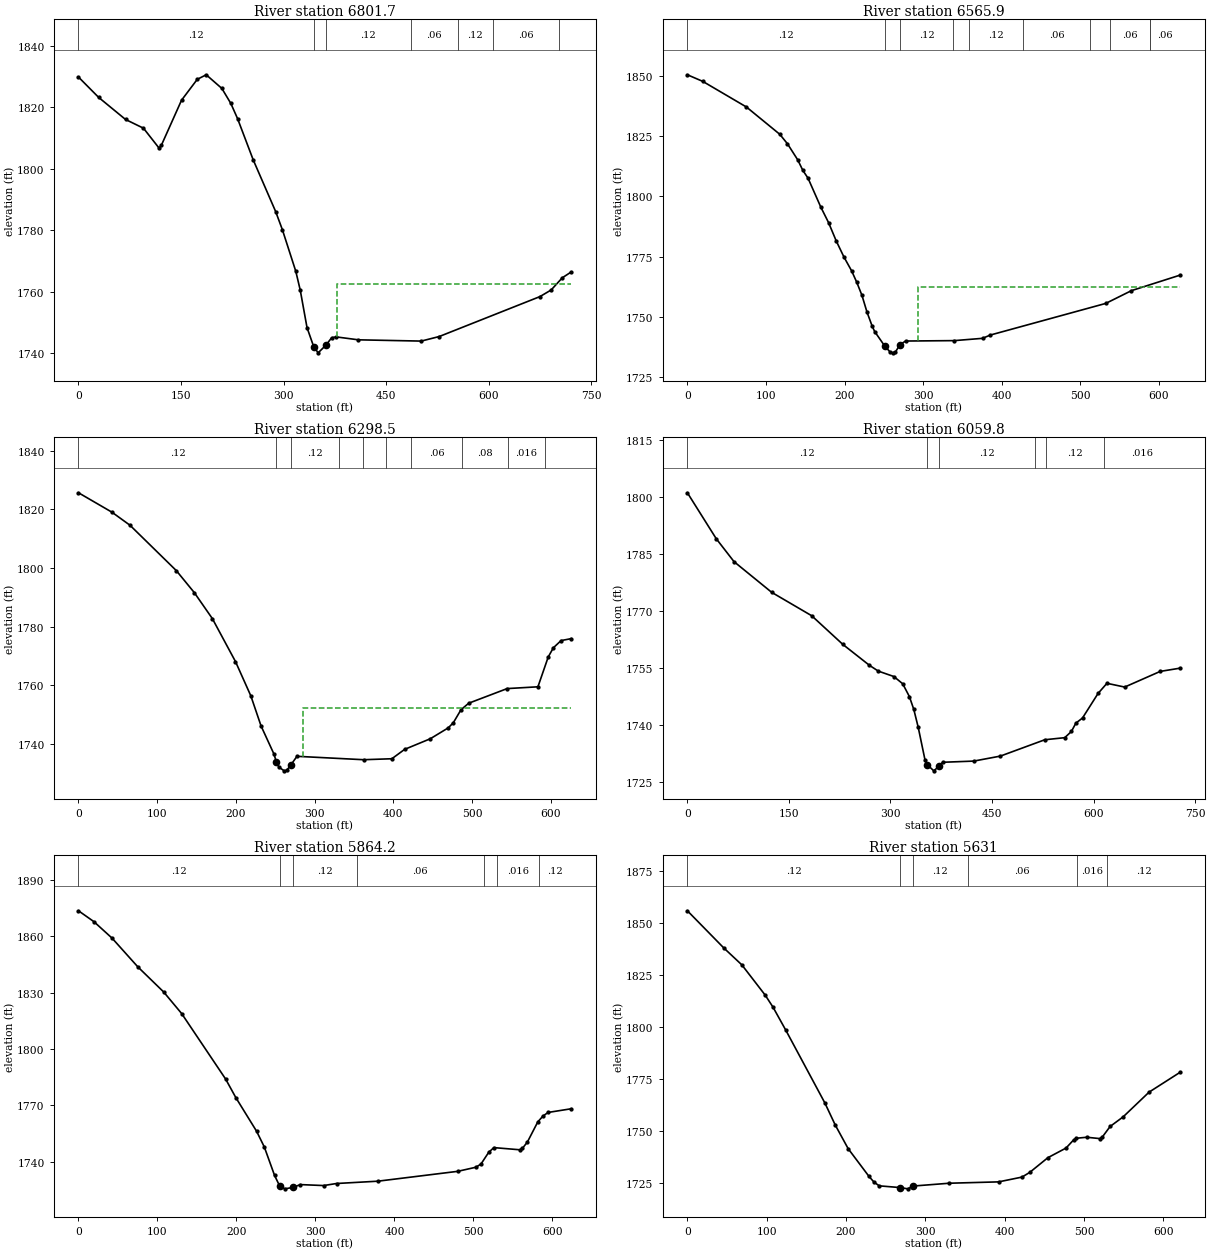
Type RM Length L Ch R = 1 ,6801.7  ,240.2,235.9,231.1
XS GIS Cut Line= 3
     2034817.368      145171.775     2034633.774      145174.379
     2034281.396      145580.183
#Sta/Elev= 30
       0 1829.81    29.5 1823.21    68.8 1816.04    95.1 1813.19     118  1806.7
   121.3 1807.66   150.8  1822.3   173.8 1829.08   186.9 1830.56   209.8 1826.12
   222.9 1821.25   232.8 1816.29   255.7 1802.88   288.5  1786.1   298.3 1780.23
     318 1766.66   324.5 1760.54   334.4 1748.38   344.2 1742.17   350.7 1740.18
   362.1 1742.69   370.4 1745.07     377 1745.36   409.7 1744.41   501.5    1744
   527.7 1745.47   675.2 1758.46   691.6 1760.61     708 1764.59   721.1 1766.48
#Mann= 7 ,-1 , 0
       0     .12       0   344.2    .045       0   362.1     .12       0
   485.9     .06       0   554.7     .12       0   606.1     .06       0
   703.2     .08       0
#XS Ineff= 2 , 0
                          378.97         1762.62
Permanent Ineff=
       F       F
Bank Sta=344.2,362.1
XS Rating Curve= 0 ,0
Exp/Cntr=0.3,0.1

Type RM Length L Ch R = 1 ,6565.9  ,262.2,267.4,272.3
XS GIS Cut Line= 2
     2034465.805      144934.796     2034155.735      145479.896
#Sta/Elev= 30
       0 1850.56    19.6 1847.81    75.1 1837.17   117.6 1825.81   127.4 1821.85
   140.4  1815.2     147 1810.77   153.5 1807.59   169.8 1795.54   179.6 1789.14
   189.4 1781.49   199.2 1774.82     209 1769.04   215.6 1764.25   222.1  1758.9
   228.6 1751.86   235.2 1746.01   238.4 1743.78   251.5 1737.62     258 1735.31
   261.3 1734.96   264.6 1735.24   270.5 1738.34   277.6 1739.87   339.7 1740.04
   375.6 1740.99   385.4 1742.35   532.4 1755.51   565.1 1760.82   627.1 1767.28
#Mann= 10 ,-1 , 0
       0     .12       0   251.5    .045       0   270.5     .12       0
   338.3     .06       0     358     .12       0   427.1     .06       0
   512.6     .12       0   537.6     .06       0   588.2     .12       0
   588.6     .06       0
#XS Ineff= 2 , 0
                          293.61         1762.17
Permanent Ineff=
       F       F
Bank Sta=251.5,270.5
XS Rating Curve= 0 ,0
Exp/Cntr=0.3,0.1

Type RM Length L Ch R = 1 ,6298.5  ,237.7,238.7,239.5
XS GIS Cut Line= 3
     2034339.546      144859.362     2034175.484      144947.903
     2033879.153      145272.811
#Sta/Elev= 30
       0 1825.71    42.5 1819.08    65.4 1814.63   124.3 1799.13   147.2  1791.6
   170.1 1782.74   199.5 1768.06     219 1756.35     232 1746.07   248.3 1736.52
   251.6  1733.7   254.6 1732.03   261.4 1730.75   264.6 1730.92   269.6 1732.67
   277.6 1735.71   362.3 1734.55   398.2 1734.88   414.4 1738.08     447  1741.7
   469.8 1745.42   476.3 1747.18   486.1 1751.64   495.9 1753.85   544.7 1758.84
   583.8 1759.45   596.9 1769.64   603.4 1772.77   613.2 1775.23   626.2 1775.91
#Mann= 10 ,-1 , 0
       0     .12       0   251.6    .045       0   269.6     .12       0
   330.5     .08       0   361.1     .06       0   390.9     .12       0
   423.1     .06       0   487.1     .08       0     546    .016       0
   592.6     .12       0
#XS Ineff= 2 , 0
                           285.7         1752.14
Permanent Ineff=
       F       F
Bank Sta=251.6,269.6
XS Rating Curve= 0 ,0
Exp/Cntr=0.3,0.1

Type RM Length L Ch R = 1 ,6059.8  ,203.1,195.6,188.2
XS GIS Cut Line= 3
     2034207.317      144580.939     2033951.298      144839.686
     2033695.279      145098.434
#Sta/Elev= 30
       0  1801.2    42.6 1789.09    68.9 1783.03   124.6 1774.93   183.6 1768.77
   229.6 1761.21   268.9 1755.69     282 1754.16     305 1752.73   318.1 1750.82
   327.9 1747.46   334.5 1744.04     341 1739.34   350.9 1730.84   354.2 1729.51
     364 1727.85   371.5 1729.03   377.1 1730.11     423 1730.42   462.4 1731.74
     528 1736.05   557.5  1736.6   567.3 1738.24   573.9 1740.43   583.7 1741.79
   606.7 1748.27   619.8 1750.94     646 1749.95   698.5 1754.08     728 1754.94
#Mann= 6 ,-1 , 0
       0     .12       0   354.2    .045       0   371.5     .12       0
   513.5    .016       0   530.2     .12       0   614.9    .016       0
Bank Sta=354.2,371.5
XS Rating Curve= 0 ,0
Exp/Cntr=0.3,0.1

Type RM Length L Ch R = 1 ,5864.2  ,230.1,233.2,236
XS GIS Cut Line= 2
     2033925.441      144467.348     2033653.434      145028.731
#Sta/Elev= 30
       0 1873.52    19.6  1867.7    42.5 1858.95    75.1 1843.66   107.8  1830.3
   130.6 1818.79   186.2 1783.96   199.2 1774.02   225.4 1756.17   235.2 1747.78
   248.2 1732.61   254.8 1726.87   261.3 1725.48   271.4 1726.24   280.9 1727.74
   310.3 1727.23   326.6 1728.32   378.9 1729.55   480.1  1734.8     503 1736.98
   509.5  1738.7   519.3 1744.95   525.8 1747.43   558.5 1746.28   561.8 1746.96
   568.3 1750.45   581.4 1761.13   587.9 1764.21   594.4 1766.15   623.8 1768.12
#Mann= 7 ,-1 , 0
       0     .12       0   254.8    .045       0   271.4     .12       0
     352     .06       0   513.2     .12       0   529.9    .016       0
   582.6     .12       0
Bank Sta=254.8,271.4
XS Rating Curve= 0 ,0
Exp/Cntr=0.3,0.1

Type RM Length L Ch R = 1 ,5631    ,179,186.9,199.6
XS GIS Cut Line= 2
     2033743.149      144393.129     2033404.607      144913.962
#Sta/Elev= 30
       0  1856.1    45.8 1838.26    68.7 1830.08    98.1 1815.54   107.9 1809.79
   124.2 1798.59   173.3 1763.71   186.4 1753.09   202.7 1741.71   228.9  1728.4
   235.4 1725.58   241.9 1723.85   268.1 1723.02   277.9 1722.41   283.9 1723.73
   330.2 1725.11   392.3 1725.76   421.8 1728.06   431.6 1730.33   454.4 1737.38
   477.3 1742.02   487.1 1746.02   490.4 1746.74   503.5 1747.21   519.8 1746.57
   523.1 1747.35   532.9  1752.4   549.3 1757.02     582 1768.91   621.2 1778.47
#Mann= 6 ,-1 , 0
       0     .12       0   268.1    .045       0   283.9     .12       0
   353.3     .06       0   491.1    .016       0   528.8     .12       0
Bank Sta=268.1,283.9
XS Rating Curve= 0 ,0
Exp/Cntr=0.3,0.1

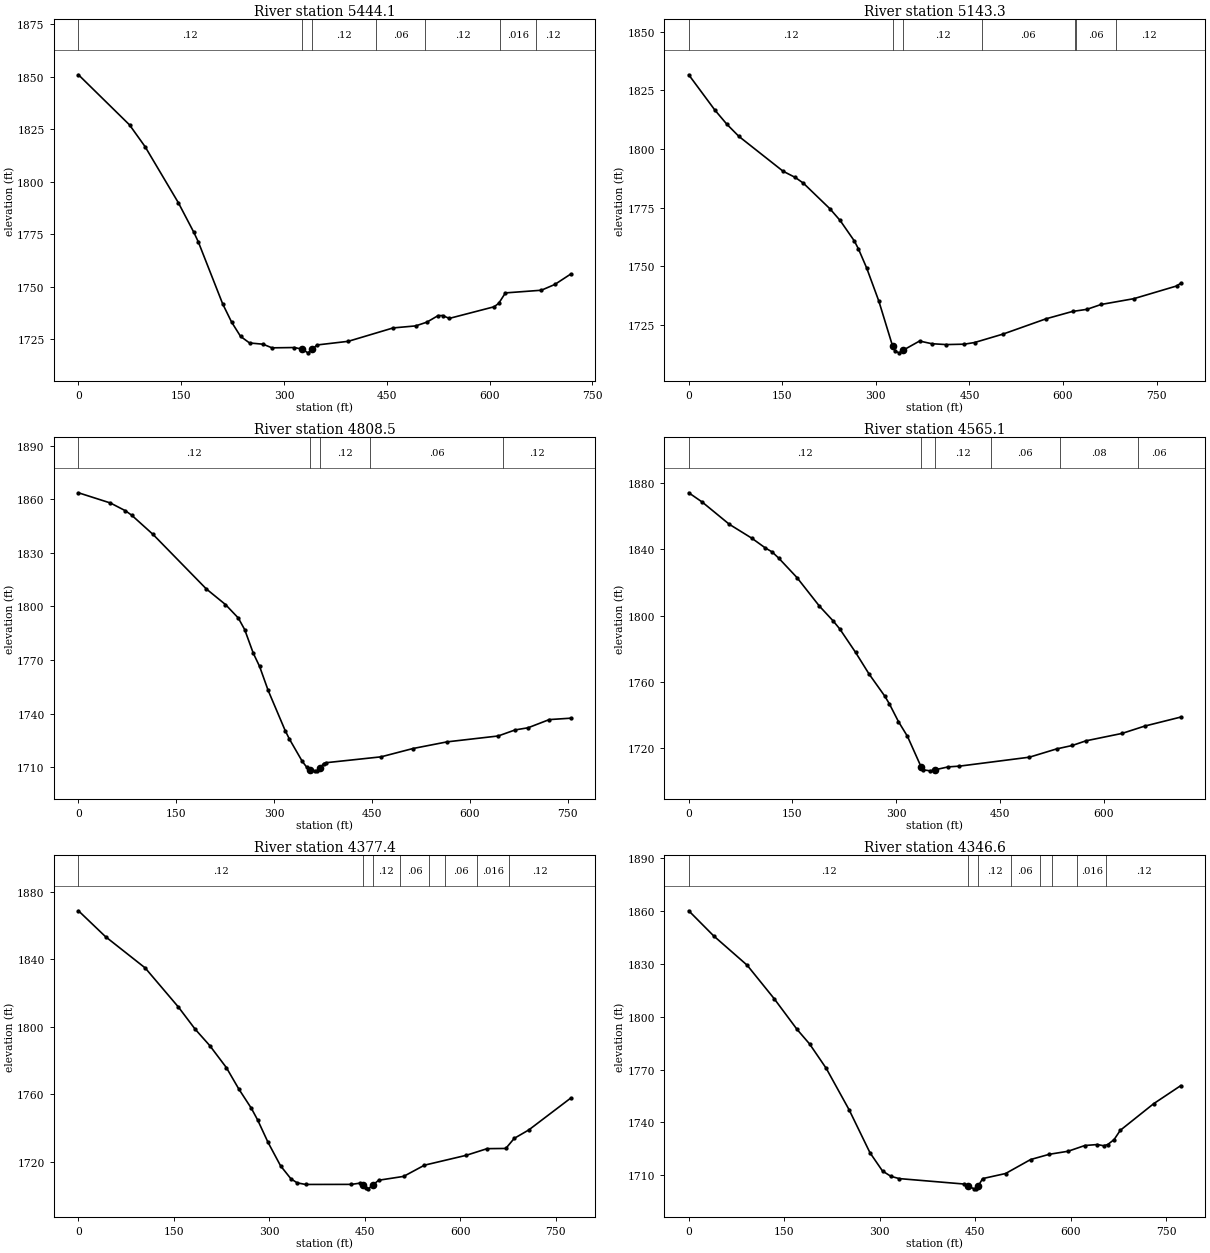
Type RM Length L Ch R = 1 ,5444.1  ,295.4,300.8,300.5
XS GIS Cut Line= 3
     2033718.409      144351.462     2033538.722      144484.275
     2033086.111      144683.491
#Sta/Elev= 30
       0 1850.86    74.5    1827    97.2 1816.63   145.7 1789.95   168.4 1775.78
   174.9 1771.25   210.5 1741.68   223.4 1733.09   236.5 1726.26   249.6 1723.12
   269.3 1722.52   282.4 1720.79   315.1 1720.94   326.4 1720.16   334.8 1718.41
   341.4 1720.08   347.9 1722.15   393.7  1723.9   459.2 1730.28     492 1731.24
   508.4 1733.03   524.7 1736.13   531.3 1736.19   541.1 1734.81   606.6 1740.36
   613.2 1741.99     623 1746.96   675.4 1748.23     695 1750.97     718 1755.87
#Mann= 7 ,-1 , 0
       0     .12       0   326.4    .045       0   341.4     .12       0
   434.4     .06       0   505.2     .12       0   615.7    .016       0
   667.2     .12       0
Bank Sta=326.4,341.4
XS Rating Curve= 0 ,0
Exp/Cntr=0.3,0.1

Type RM Length L Ch R = 1 ,5143.3  ,358.5,334.8,310.8
XS GIS Cut Line= 4
     2033684.555      144179.587     2033533.671      144169.316
     2033227.524      144316.306     2033081.586      144576.035
#Sta/Elev= 30
       0 1831.63    41.8 1816.62    61.1 1810.56    80.4 1805.38   151.2 1790.54
   170.8 1787.88   183.9 1785.41   226.3 1774.54   242.7 1769.54   265.5  1760.8
     272 1757.45   285.1 1749.38   304.7 1735.21   326.9 1715.93   330.8 1713.82
   337.4 1713.15   343.9  1714.3     370 1718.18   389.6 1717.04   412.5 1716.67
   441.9 1716.84   458.2 1717.55   503.9 1721.15   572.7 1727.65   615.2 1730.79
   638.2 1731.68   661.1 1733.76   713.5 1736.23   782.2 1741.65   788.8 1742.82
#Mann= 7 ,-1 , 0
       0     .12       0   326.9    .045       0   343.9     .12       0
   469.7     .06       0   618.4     .12       0   620.7     .06       0
   685.6     .12       0
Bank Sta=326.9,343.9
XS Rating Curve= 0 ,0
Exp/Cntr=0.3,0.1

Type RM Length L Ch R = 1 ,4808.5  ,246.4,243.4,240.1
XS GIS Cut Line= 3
     2033118.068      143755.755     2033082.993      144264.223
     2033000.961      144494.692
#Sta/Elev= 30
       0 1863.57      49 1857.85    71.9 1853.53    81.7 1850.99   114.4 1840.24
     196 1809.76   225.4 1801.01     245  1793.5   254.8    1787   267.9 1773.86
   277.7 1766.35   290.8 1752.94   316.9 1730.47   323.4 1725.72     343  1713.3
   349.6 1710.13   355.4 1708.36   362.6 1707.95   365.9 1708.12   370.4 1709.49
   375.7 1712.02     379 1712.48   463.9 1715.79   512.9 1720.45   565.1 1724.17
   643.4 1727.46   669.5 1730.86   689.1 1732.04   721.7 1736.63   754.3 1737.41
#Mann= 5 , 0 , 0
       0     .12       0   355.4    .045       0   370.4     .12       0
   447.4     .06       0   651.5     .12       0
Bank Sta=355.4,370.4
XS Rating Curve= 0 ,0
Exp/Cntr=0.3,0.1

Type RM Length L Ch R = 1 ,4565.1  ,181.5,187.7,193.6
XS GIS Cut Line= 3
     2032948.878      143770.733     2032846.013      144010.317
     2032878.426      144459.791
#Sta/Elev= 30
       0 1874.26    19.6 1868.61    58.7  1855.2    91.3 1846.77   110.8 1840.89
   120.6 1838.49   130.4 1834.62   156.4 1823.04     189  1805.7   208.6 1796.89
   218.4 1791.92   241.2 1777.78   260.7  1764.7   283.6 1751.23   290.1 1746.64
   303.2 1735.92   316.2 1727.04   336.1 1708.44   339.1  1706.8   348.9 1706.18
   355.4 1706.74     375 1708.57   391.4 1709.02   492.6 1714.44   531.8 1719.43
   554.6 1721.52   574.2 1724.32   626.5 1728.81   659.1 1733.22   711.4 1738.69
#Mann= 6 ,-1 , 0
       0     .12       0   336.1    .045       0   355.4     .12       0
   436.8     .06       0   536.1     .08       0   648.9     .06       0
Bank Sta=336.1,355.4
XS Rating Curve= 0 ,0
Exp/Cntr=0.3,0.1

Type RM Length L Ch R = 1 ,4377.4  ,30.9,30.7,30.9
XS GIS Cut Line= 3
     2032922.533      143771.211     2032696.216      143994.004
     2032607.588       144441.01
#Sta/Elev= 30
       0 1868.73    42.6 1853.37   104.8 1834.89   157.2 1811.65   183.3 1798.63
   206.3 1788.89   232.4 1775.86   252.1 1763.09   271.7 1751.74   281.6 1744.82
   297.9 1731.57   317.6 1717.67     334 1709.92   343.8 1707.56   356.9 1706.62
     429 1706.66   442.2 1707.38   447.3 1706.47     452 1704.36   455.3 1704.02
   462.3 1706.14   471.7 1709.11     511 1711.39   543.8 1718.04   609.4 1723.88
   642.2 1727.82   671.6 1727.94   684.8 1733.91   707.7 1738.91   773.3 1757.68
#Mann= 8 ,-1 , 0
       0     .12       0   447.3    .045       0   462.3     .12       0
   504.9     .06       0   551.2     .12       0     576     .06       0
   626.1    .016       0     676     .12       0
Bank Sta=447.3,462.3
XS Rating Curve= 0 ,0
Exp/Cntr=0.3,0.1

Type RM Length L Ch R = 1 ,4346.6  ,38.5,43,47.3
XS GIS Cut Line= 3
     2032891.066      143772.296     2032664.749      143995.089
     2032576.121      144442.095
#Sta/Elev= 30
       0 1860.25    39.3 1845.95    91.7 1829.37   134.2 1810.35   170.2 1792.88
   189.9 1784.61   216.1 1770.73   252.1 1747.17   284.8 1722.83   304.5 1712.46
   317.6 1709.44   330.7 1708.14   432.3 1705.06   439.3 1703.74   448.7 1702.32
     452 1702.47   455.3 1704.17   461.8 1708.13   497.9 1711.02   537.2 1718.95
   566.7 1721.95   596.2 1723.67   622.5 1726.93   642.2 1727.48     652  1726.8
   658.5  1727.5   668.4 1730.27   678.2 1735.57   730.7  1750.7   773.3 1760.96
#Mann= 8 ,-1 , 0
       0     .12       0   439.3    .045       0   455.3     .12       0
   505.7     .06       0   551.8     .08       0     571     .06       0
   610.5    .016       0   656.2     .12       0
Bank Sta=439.3,455.3
XS Rating Curve= 0 ,0
Exp/Cntr=0.3,0.1

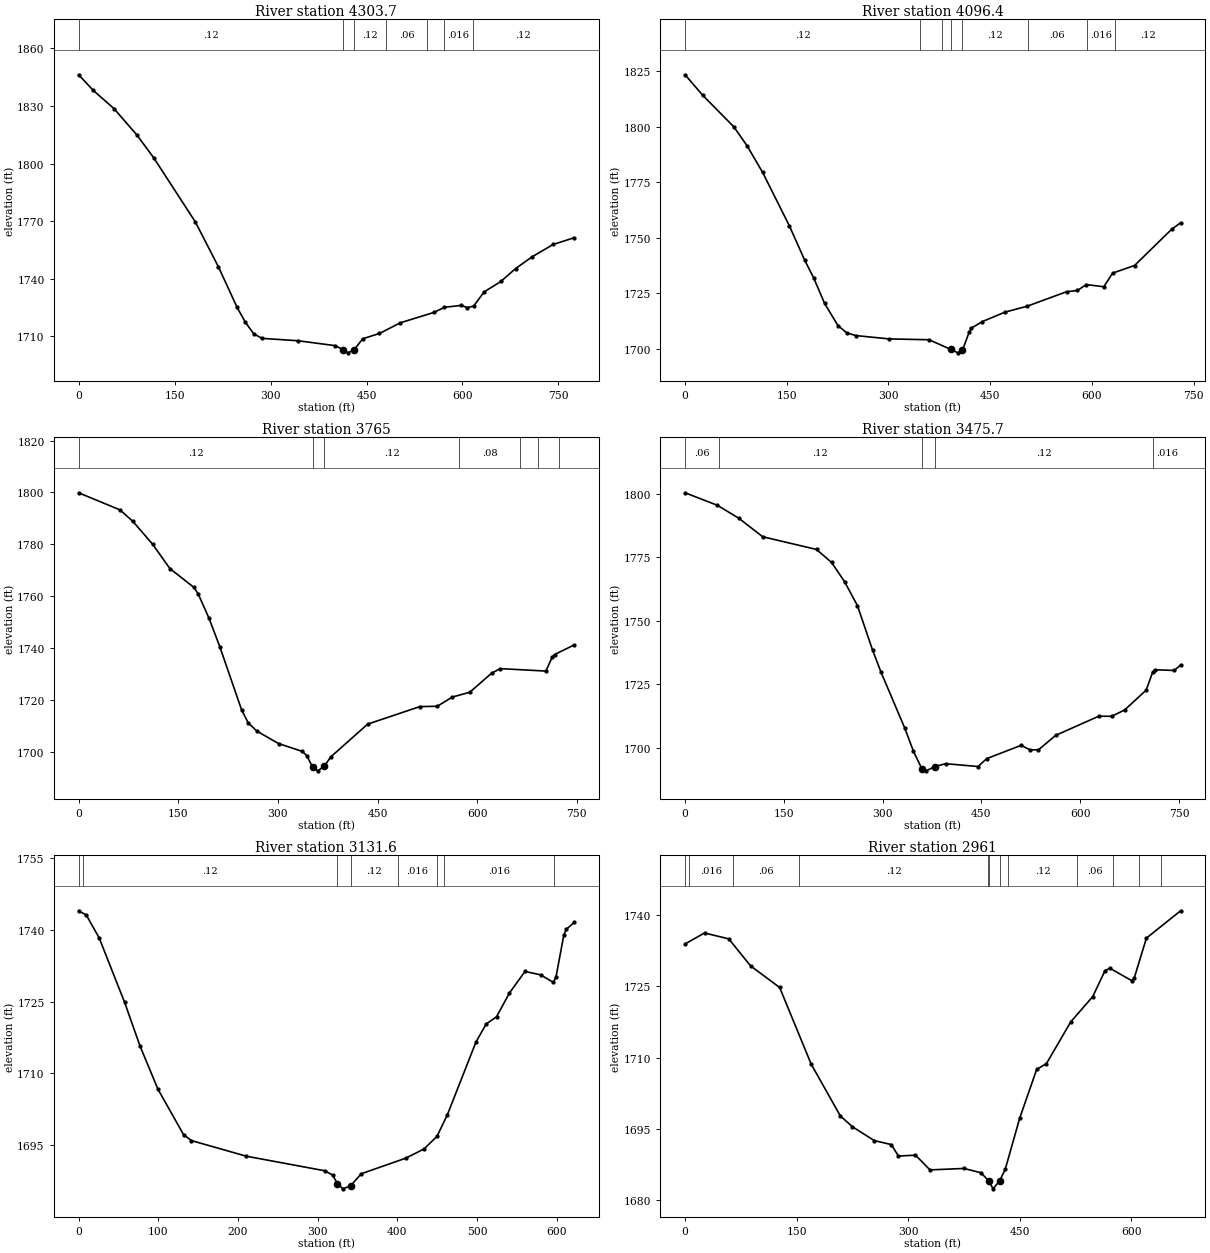
Type RM Length L Ch R = 1 ,4303.7  ,191.1,207.3,223.3
XS GIS Cut Line= 3
     2032847.316      143773.337     2032652.003      143979.067
     2032465.029      144432.964
#Sta/Elev= 30
       0 1846.21    22.8 1838.09    55.4 1828.56    91.3 1814.75   117.4 1802.97
   182.6 1769.51   218.5 1746.22   247.8 1725.04   260.8 1717.28   273.9 1711.25
     287 1708.95   342.6 1707.74   401.5 1705.16   413.7 1702.98   421.1 1701.43
   430.9 1703.15     444 1708.74   470.2 1711.51   502.9 1717.08   555.3 1722.46
   571.7 1725.13   597.8 1726.13   607.7 1724.98   617.5 1725.78   633.8 1733.15
     660 1738.58   682.9 1745.28   709.1 1751.49   741.8 1757.86   774.6 1761.37
#Mann= 7 ,-1 , 0
       0     .12       0   413.7    .045       0   430.9     .12       0
   480.9     .06       0   544.5     .08       0   571.5    .016       0
   615.8     .12       0
Bank Sta=413.7,430.9
XS Rating Curve= 0 ,0
Exp/Cntr=0.3,0.1

Type RM Length L Ch R = 1 ,4096.4  ,344.7,331.3,317.4
XS GIS Cut Line= 4
     2032766.586      143751.202     2032596.013      143903.546
     2032341.036      144031.797     2032246.578      144226.983
#Sta/Elev= 30
       0 1823.49    26.1 1814.22    71.9 1800.03    91.5 1791.47   114.4 1779.47
   153.6 1755.56   176.4 1739.94   189.5 1732.07   205.8 1720.46   225.4 1710.48
   238.5 1707.18   251.7 1705.97   300.9 1704.46   359.9 1704.08   392.1  1699.7
   402.6 1698.18   409.1 1699.28     419  1707.5   422.3 1709.34   438.7 1712.29
   471.5 1716.48   504.3 1719.17   562.7 1725.71   578.8 1726.29   591.8 1728.94
   617.7 1727.96   630.6  1734.1     663 1737.54     718 1753.94     731 1756.78
#Mann= 8 ,-1 , 0
       0     .12       0   346.7     .06       0   378.5     .12       0
   392.1    .045       0   409.1     .12       0   505.2     .06       0
   592.6    .016       0   634.3     .12       0
Bank Sta=392.1,409.1
XS Rating Curve= 0 ,0
Exp/Cntr=0.3,0.1

Type RM Length L Ch R = 1 ,3765    ,290.1,289.3,285.9
XS GIS Cut Line= 2
     2032415.625      143429.007     2032074.574      144092.576
#Sta/Elev= 30
       0 1799.87    62.2 1793.29    81.8 1788.81   111.3 1780.09   137.4 1770.67
   173.4 1763.46     180 1760.91   196.3 1751.53   212.7 1740.47   245.4 1716.22
   255.2 1711.29   268.3 1708.06     301 1703.26     337 1700.21   343.6 1698.55
  352.16 1694.23     360 1692.75   369.8  1694.5   379.6 1698.12   435.2 1710.75
   513.8  1717.5   539.9 1717.62   562.8 1721.18     589 1723.04   621.7 1730.34
   634.8 1732.13   703.5 1731.18   713.4 1736.77   716.6 1737.54   746.1 1741.26
#Mann= 7 ,-1 , 0
       0     .12       0  352.16    .045       0   369.8     .12       0
   573.1     .08       0   664.2    .016       0     692     .08       0
   723.5     .12       0
Bank Sta=352.16,369.8
XS Rating Curve= 0 ,0
Exp/Cntr=0.3,0.1

Type RM Length L Ch R = 1 ,3475.7  ,361.8,344.1,326.5
XS GIS Cut Line= 2
     2032120.753       143287.66     2031887.323      144003.018
#Sta/Elev= 30
       0 1800.42    49.1 1795.48    81.8 1790.34   117.8  1783.1   199.6 1778.08
   222.5 1772.95   242.1 1765.41   261.7 1755.95   284.6 1738.49   297.7  1729.6
   333.7 1707.59   346.8 1698.53   359.9 1691.46   366.4 1690.84   378.8 1692.52
   395.9 1693.66   444.9 1692.54     458 1695.66   510.4  1700.9   523.5 1699.13
   536.6  1699.1   562.7 1704.82   628.2 1712.37   647.8 1712.34   667.4 1714.82
   700.1 1722.62     710 1729.71   713.2 1730.67   742.7  1730.4   752.5 1732.56
#Mann= 5 , 0 , 0
       0     .06       0    50.9     .12       0   359.9    .045       0
   378.8     .12       0   709.8    .016       0
Bank Sta=359.9,378.8
XS Rating Curve= 0 ,0
Exp/Cntr=0.3,0.1

Type RM Length L Ch R = 1 ,3131.6  ,159.8,170.6,180.8
XS GIS Cut Line= 4
     2031633.817      143390.612     2031627.263      143515.525
     2031768.778       143814.95     2031751.786      143979.587
#Sta/Elev= 30
       0 1743.92     9.6 1743.03    25.7 1738.29    57.7 1724.83      77 1715.74
    99.4 1706.76   131.6 1697.27   141.5 1696.01   210.3 1692.76   308.7 1689.72
   318.6 1688.84   324.7 1687.06   331.7 1685.95   341.5 1686.62   354.6 1689.09
   410.4 1692.34   433.3 1694.26   449.7 1696.89   462.8 1701.44   498.5 1716.53
   511.4 1720.32   524.4 1721.82   540.6 1726.78   560.1 1731.27   579.6 1730.57
   595.8 1728.98   599.1 1730.21   608.8 1738.86     612 1740.07   621.8 1741.49
#Mann= 8 ,-1 , 0
       0     .08       0     5.9     .12       0   324.7    .045       0
   341.5     .12       0   400.2    .016       0   449.6     .12       0
   458.7    .016       0   596.4     .08       0
Bank Sta=324.7,341.5
XS Rating Curve= 0 ,0
Exp/Cntr=0.3,0.1

Type RM Length L Ch R = 1 ,2961    ,317.7,304.1,290.6
XS GIS Cut Line= 3
     2031565.465      143344.998     2031558.253       143837.14
     2031542.628      144010.317
#Sta/Elev= 30
       0 1733.96    26.1 1736.27    58.7 1735.03      88 1729.34   127.1 1724.78
   169.5 1708.62   208.6 1697.73   224.9 1695.43   254.2 1692.52   277.1 1691.67
   286.8 1689.25   309.7 1689.44   329.2 1686.33   374.8 1686.64   397.7 1685.73
     408 1684.04     414 1682.34     423 1684.09   430.3 1686.45   449.8 1697.25
   472.6 1707.52   485.7 1708.73   518.4 1717.54     548 1722.88   564.4 1728.31
   570.9 1728.85   600.5 1726.21   603.7 1726.76   620.1 1735.19   666.1 1740.95
#Mann= 12 ,-1 , 0
       0     .06       0     5.4    .016       0    64.6     .06       0
   153.5     .12       0   407.6    .016       0     408    .045       0
     423    .016       0     434     .12       0   527.4     .06       0
   574.9    .016       0   609.9     .12       0   639.5     .06       0
Bank Sta=408,423
XS Rating Curve= 0 ,0
Exp/Cntr=0.3,0.1