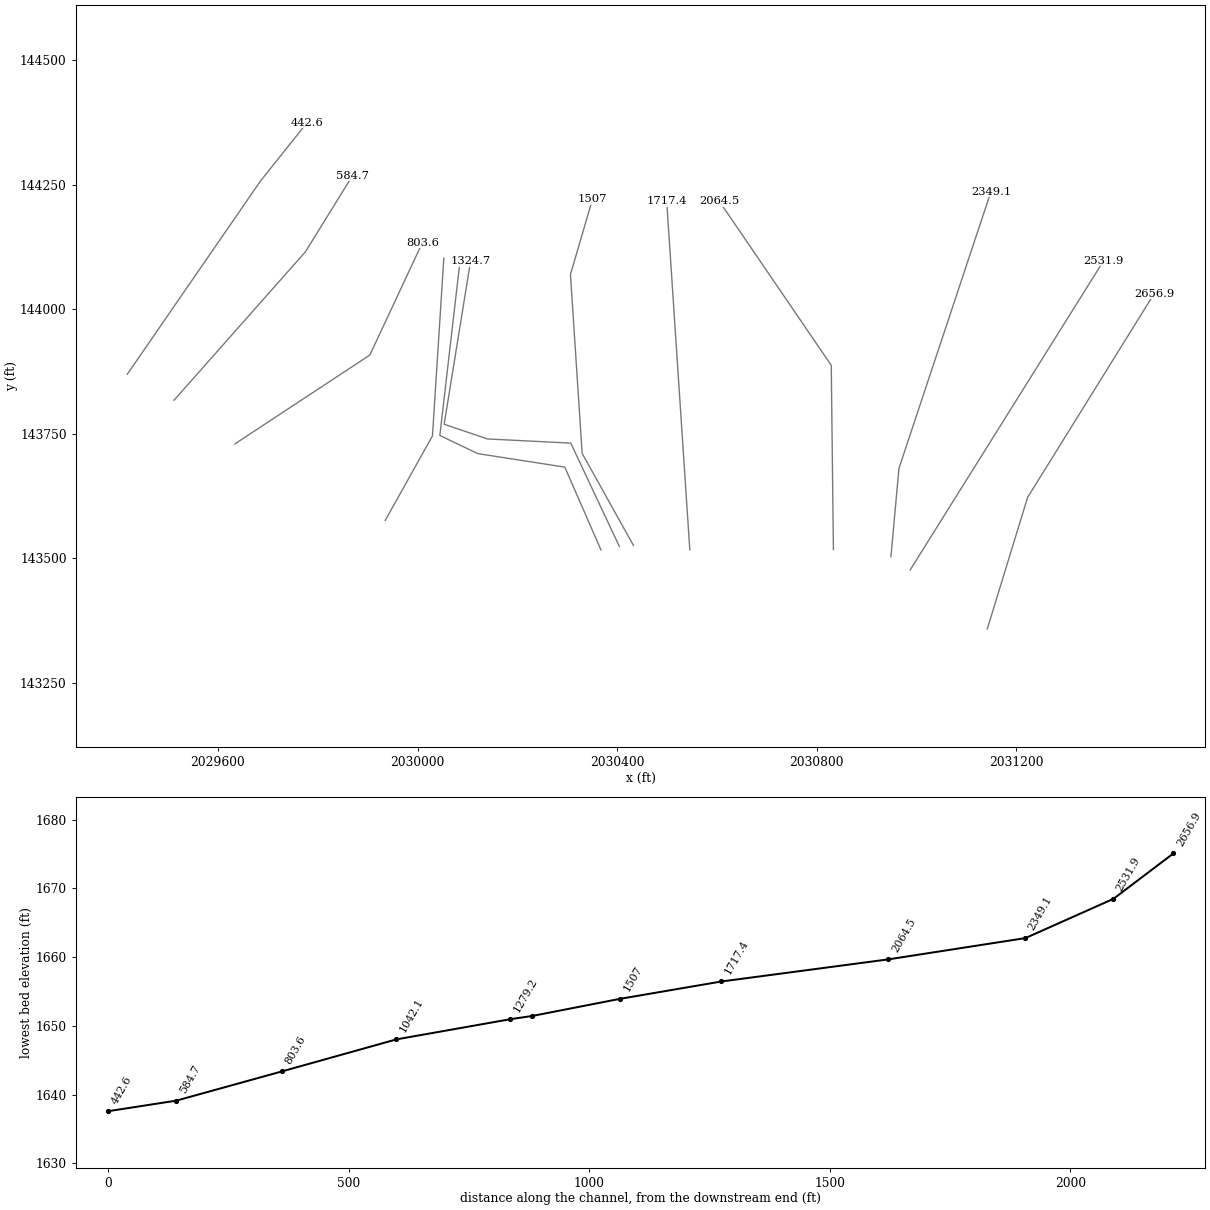
HEC-RAS study SCOTTBR.prj: SCOTTBR

--- SCOTTBR.g01 (geometry) --- (continued)

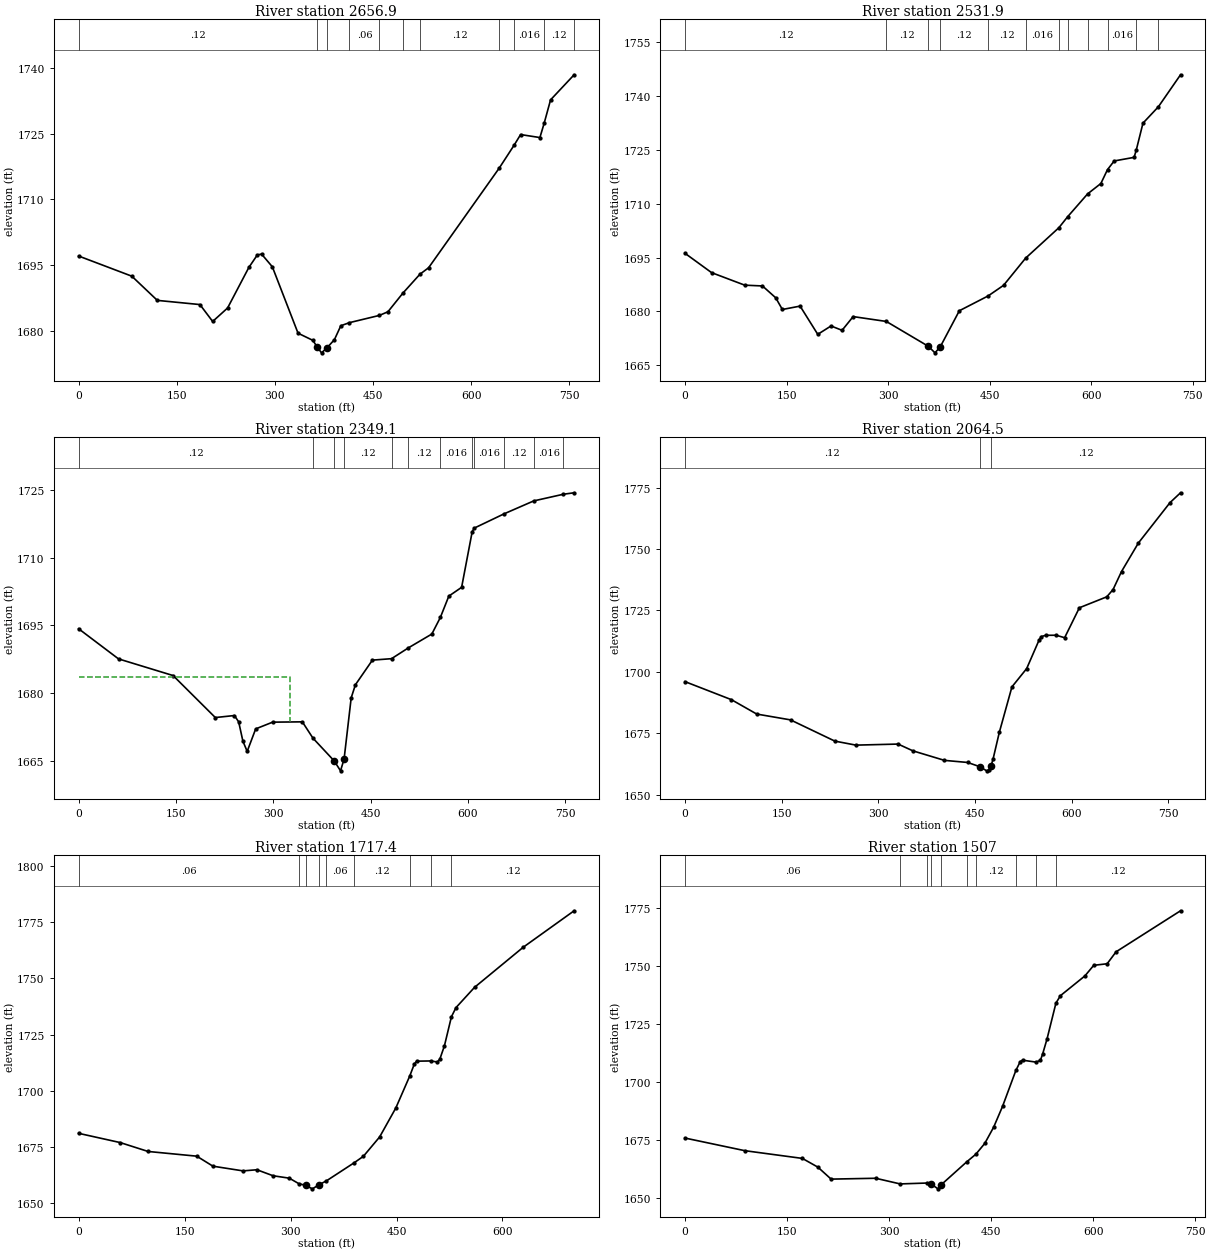
Type RM Length L Ch R = 1 ,2656.9  ,125,125,125.2
XS GIS Cut Line= 3
     2031141.465      143357.924     2031222.316      143622.296
     2031475.712       144031.09
#Sta/Elev= 30
       0 1697.13    81.3 1692.54   120.3 1687.03   185.4 1686.08   204.9 1682.23
   227.7  1685.3   260.2 1694.53   273.2 1697.39   279.7 1697.56   296.1 1694.68
   335.4 1679.56   358.2 1677.92   364.3 1676.47   371.3 1675.09   379.3 1676.18
     391 1678.09   400.8 1681.26   413.9 1681.96   459.7 1683.61   472.8 1684.44
   495.7 1688.69   521.8    1693   534.9 1694.45   642.9 1717.14   665.8 1722.39
   675.6 1724.78   705.1  1724.1   711.6 1727.35   721.4 1732.68   757.4 1738.39
#Mann= 11 ,-1 , 0
       0     .12       0   364.3    .045       0   379.3     .12       0
   413.9     .06       0   459.7    .016       0   495.7     .06       0
   521.8     .12       0   642.9     .06       0   665.8    .016       0
   711.6     .12       0   757.4     .06       0
Bank Sta=364.3,379.3
XS Rating Curve= 0 ,0
Exp/Cntr=0.3,0.1

Type RM Length L Ch R = 1 ,2531.9  ,177.5,182.8,187.9
XS GIS Cut Line= 2
      2030986.97      143476.527     2031374.659      144097.556
#Sta/Elev= 30
       0 1696.17    39.2  1690.8    88.2 1687.31   114.4 1687.09     134 1683.79
   143.8 1680.54     170 1681.48   196.1 1673.62   215.7 1675.95     232 1674.74
   248.4 1678.56   297.4 1677.21   359.5 1670.29   369.3 1668.47     377 1670.11
   405.3 1680.19   447.8 1684.31   470.6 1687.26   503.3 1694.85   552.4 1703.31
   565.4 1706.38   594.8 1712.72   614.4 1715.61   624.2 1719.48   634.1 1721.89
   663.5 1722.89   666.7 1724.92   676.6 1732.41   699.4 1736.98   732.1 1745.88
#Mann= 12 ,-1 , 0
       0     .12       0   297.4     .12       0   359.5    .045       0
     377     .12       0   447.8     .12       0   503.3    .016       0
   552.4     .06       0   565.4     .12       0   594.8     .06       0
   624.2    .016       0   666.7     .12       0   699.4     .06       0
Bank Sta=359.5,377
XS Rating Curve= 0 ,0
Exp/Cntr=0.3,0.1

Type RM Length L Ch R = 1 ,2349.1  ,262.5,284.5,304.2
XS GIS Cut Line= 3
     2030948.467      143503.214     2030964.503      143680.455
     2031148.931      144236.374
#Sta/Elev= 30
       0 1694.26    61.5 1687.58   145.6 1683.89   210.7 1674.58   240.1 1675.03
   246.7 1673.62   253.2 1669.34   259.8 1667.08   272.9 1672.07     299 1673.56
   344.8 1673.63   361.2 1670.01   393.9 1664.97   403.7 1662.77  409.181665.411
   420.1 1678.95   426.6 1681.85   452.8 1687.31   482.3 1687.63   508.4 1690.04
   544.4 1693.09   557.5 1696.76   570.6  1701.5   590.3 1703.44   606.6 1715.78
   609.9 1716.58   655.7 1719.73   701.5  1722.6   747.3 1724.08   763.7  1724.4
#Mann= 12 ,-1 , 0
       0     .12       0   361.2     .12       0   393.9    .045       0
  409.18     .12       0   482.3     .08       0   508.4     .12       0
   557.5    .016       0   606.6     .06       0   609.9    .016       0
   655.7     .12       0   701.5    .016       0   747.3     .12       0
#XS Ineff= 2 , 0
          325.16  1683.5
Permanent Ineff=
       F       F
Bank Sta=393.9,409.18
XS Rating Curve= 0 ,0
Exp/Cntr=0.3,0.1

Type RM Length L Ch R = 1 ,2064.5  ,360.3,347.1,333.9
XS GIS Cut Line= 3
      2030833.21      143517.478     2030828.869      143887.487
      2030604.26      144217.348
#Sta/Elev= 30
       0    1696      72 1688.66   111.3  1682.8   163.7 1680.43   232.5 1671.79
   265.2 1670.15   330.7 1670.58   353.7 1667.82   402.7 1663.94   438.7 1663.09
   457.5 1661.37   468.2 1659.68   471.4 1659.87   474.7 1661.46     478 1664.34
   487.8 1675.33   507.4 1693.87   530.3 1701.33   549.9 1713.15   553.2 1714.37
   559.8 1714.87   576.1  1714.9   589.2 1713.89   612.1 1726.09   654.6 1730.54
   664.4 1733.52   677.5 1740.84   703.7 1752.46   752.8 1768.91   769.1 1772.91
#Mann= 3 ,-1 , 0
       0     .12       0   457.5    .045       0   474.7     .12       0
Bank Sta=457.5,474.7
XS Rating Curve= 0 ,0
Exp/Cntr=0.3,0.1

Type RM Length L Ch R = 1 ,1717.4  ,210.6,210.5,209.9
XS GIS Cut Line= 2
     2030545.449      143517.044      2030499.15      144216.892
#Sta/Elev= 30
       0 1681.13      59 1677.01    98.3 1673.07   167.2 1670.98   190.1 1666.53
   232.7 1664.44   252.4 1664.94   275.3 1662.27   298.2  1661.2   311.4 1658.82
   321.2 1657.96     331 1656.46   340.4 1658.32   350.7 1659.99     390 1668.04
   403.1 1670.92   426.1 1679.52     449 1692.39   468.7 1706.59   475.2 1711.92
   478.5  1713.2   498.2  1713.3     508 1712.84   511.3  1714.1   517.8 1720.01
   527.7 1732.92   534.2 1737.01   560.4    1746   629.3 1763.82   701.4 1780.04
#Mann= 9 ,-1 , 0
       0     .06       0   311.4     .12       0   321.2    .045       0
   340.4     .12       0   350.7     .06       0     390     .12       0
   468.7     .08       0   498.2    .016       0   527.7     .12       0
Bank Sta=321.2,340.4
XS Rating Curve= 0 ,0
Exp/Cntr=0.3,0.1

Type RM Length L Ch R = 1 ,1507    ,147.6,182.3,216.8
XS GIS Cut Line= 4
     2030432.602      143525.725     2030329.753      143710.621
     2030306.312      144069.878     2030350.354      144220.603
#Sta/Elev= 30
       0 1675.83    87.9 1670.39   172.5 1667.06   195.3  1663.3   214.8 1658.13
   280.3  1658.5   316.3 1656.06   355.6 1656.44   361.9 1655.99     372 1653.94
   376.9 1655.76   414.5 1665.65   427.6 1668.86   440.7  1673.5   453.8 1680.51
   466.9  1689.5   486.5    1705     493 1708.83   496.3  1709.4     516 1708.58
   522.5  1709.3   525.8 1712.01   532.3 1718.56   545.4 1734.02     552 1737.21
     588 1745.73     601  1750.3   620.7 1750.97   633.8 1756.12   728.6 1773.81
#Mann= 10 ,-1 , 0
       0     .06       0   316.3     .06       0   355.6     .12       0
   361.9    .045       0   376.9     .12       0   414.5     .06       0
   427.6     .12       0   486.5    .016       0     516     .08       0
   545.4     .12       0
Bank Sta=361.9,376.9
XS Rating Curve= 0 ,0
Exp/Cntr=0.3,0.1

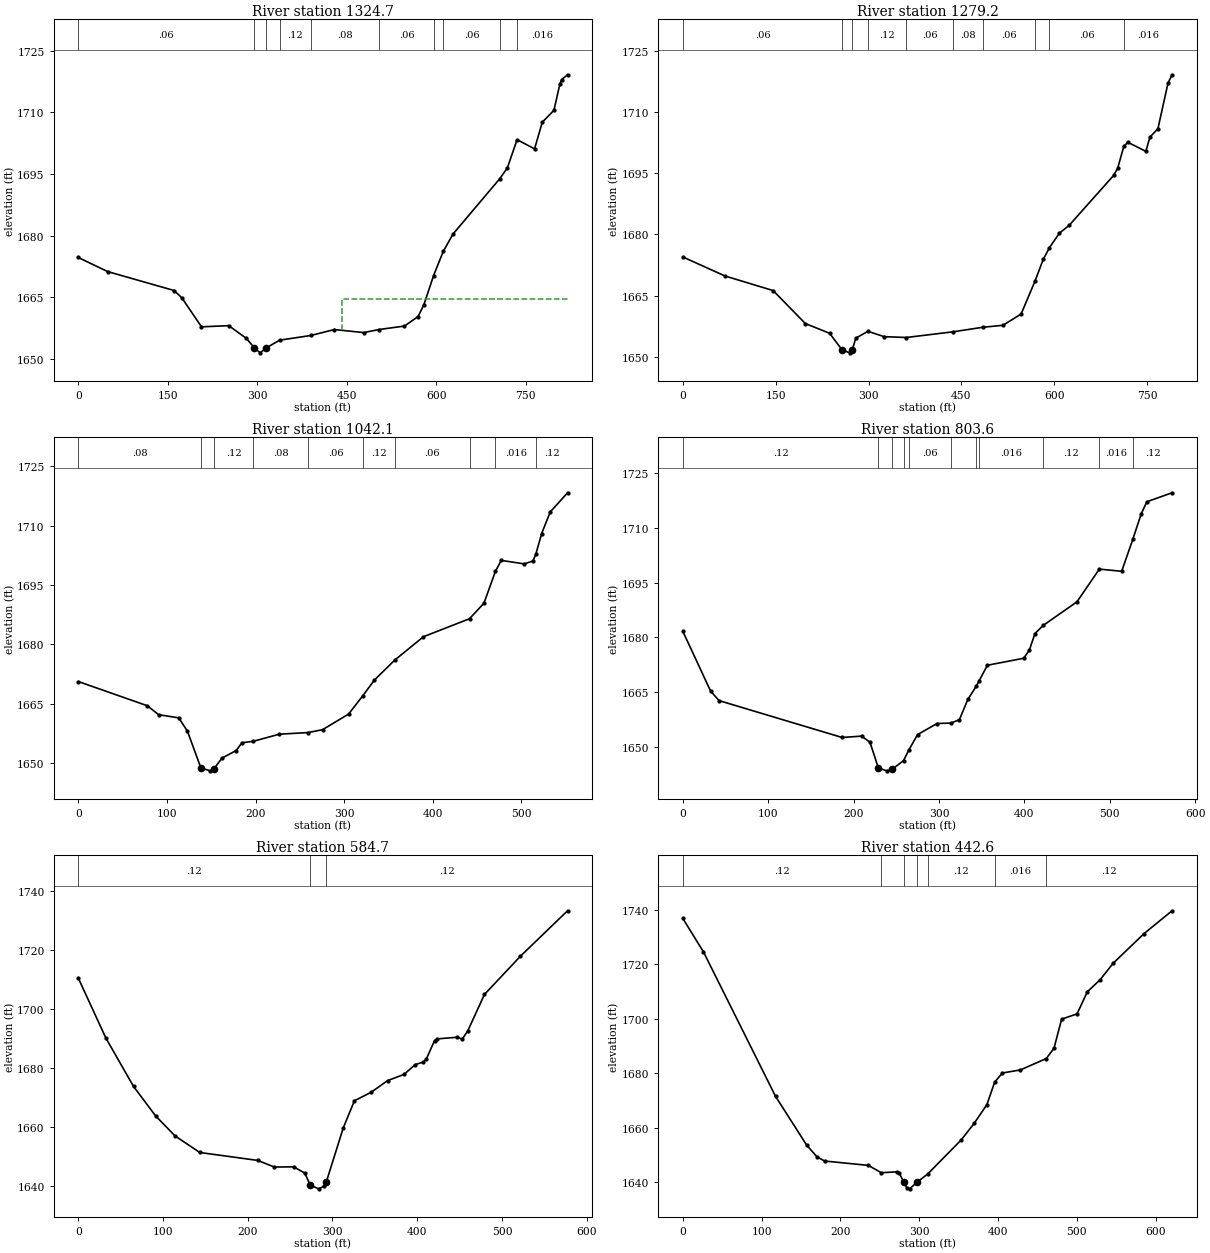
Type RM Length L Ch R = 1 ,1324.7  ,48.1,45.4,42.3
XS GIS Cut Line= 5
      2030404.39      143523.554     2030306.951      143731.237
     2030140.067      143739.621     2030053.262      143769.135
     2030106.213      144096.905
#Sta/Elev= 30
       0 1674.66    49.2 1671.23   160.6 1666.62   173.7 1664.82   206.5 1657.78
   252.3 1658.07   281.8 1654.96   294.9 1652.72   304.8 1651.45   314.6 1652.61
   337.5 1654.53     390 1655.68   429.2 1657.12   478.4 1656.38   504.5 1657.13
   546.8 1657.97   569.6 1660.28   579.3 1663.13   595.6 1670.25   611.9 1676.16
   628.2 1680.37   706.3 1693.79   719.3 1696.47   735.6 1703.34   764.9 1701.11
   777.9 1707.59   797.4  1710.5   807.2 1716.79   810.4 1717.99   820.2 1719.14
#Mann= 10 ,-1 , 0
       0     .06       0   294.9    .045       0   314.6     .12       0
   337.5     .12       0     390     .08       0   504.5     .06       0
   595.6     .12       0   611.9     .06       0   706.3     .12       0
   735.6    .016       0
#XS Ineff= 2 , 0
                          442.06          1664.5
Permanent Ineff=
       F       F
Bank Sta=294.9,314.6
XS Rating Curve= 0 ,0
Exp/Cntr=0.3,0.1

Type RM Length L Ch R = 1 ,1279.2  ,281.2,237.1,192.9
XS GIS Cut Line= 5
     2030367.498       143516.61     2030295.015       143683.06
      2030120.97      143710.107     2030044.581      143746.565
     2030084.512      144092.131
#Sta/Elev= 30
       0 1674.48    68.1 1669.82   145.9 1666.24   197.9 1658.16     237 1655.78
   257.4 1651.68   269.6 1650.98   273.9 1651.79   279.4 1654.59     299 1656.25
   325.1 1654.95   360.9 1654.74   435.8 1656.12   484.6 1657.25   517.1 1657.73
   546.4 1660.49   569.1 1668.66   582.1 1673.87   591.9  1676.7   608.1 1680.29
   624.4  1682.3   695.9 1694.48   702.4 1696.24   712.2 1701.56   718.7 1702.59
   747.9 1700.37   754.4 1703.83   767.4 1705.94   783.7 1717.11   790.2 1719.14
#Mann= 10 ,-1 , 0
       0     .06       0   257.4    .045       0   273.9     .12       0
     299     .12       0   360.9     .06       0   435.8     .08       0
   484.6     .06       0   569.1     .12       0   591.9     .06       0
   712.2    .016       0
Bank Sta=257.4,273.9
XS Rating Curve= 0 ,0
Exp/Cntr=0.3,0.1

Type RM Length L Ch R = 1 ,1042.1  ,249.3,238.5,227.5
XS GIS Cut Line= 3
     2029935.206      143576.072     2030029.824      143745.777
     2030052.611      144102.765
#Sta/Elev= 30
       0  1670.6    77.7  1664.5    90.7 1662.22   113.3 1661.43   123.1 1658.08
   138.3 1648.76     149 1648.04   153.3 1648.61   161.9 1651.23   178.1 1653.17
   184.6 1655.12   197.6 1655.52   226.8  1657.3   259.3 1657.71   275.6 1658.44
   304.9 1662.37   321.1 1667.04   334.1 1670.98   356.9 1675.99   389.4 1681.92
   441.4 1686.47   457.7  1690.4   470.7 1698.48   477.2 1701.21   503.2 1700.32
     513 1701.06   516.2 1702.74   522.8    1708   532.5 1713.44     552 1718.29
#Mann= 10 ,-1 , 0
       0     .08       0   138.3    .045       0   153.3     .12       0
   197.6     .08       0   259.3     .06       0   321.1     .12       0
   356.9     .06       0   441.4     .12       0   470.7    .016       0
   516.2     .12       0
Bank Sta=138.3,153.3
XS Rating Curve= 0 ,0
Exp/Cntr=0.3,0.1

Type RM Length L Ch R = 1 ,803.6   ,212.8,218.9,224.7
XS GIS Cut Line= 3
     2029633.991      143729.718      2029904.39      143908.103
     2030009.642      144133.797
#Sta/Elev= 30
       0 1681.66    32.7 1665.18    42.5 1662.64   186.5 1652.53   209.4  1652.9
   219.2 1651.22     229 1644.17   238.9 1643.37   245.5 1643.84   258.5 1646.19
     265 1649.21   274.9 1653.32   297.8 1656.36   314.1 1656.49   323.9  1657.4
   333.8 1662.97   343.6 1666.57   346.9 1668.02   356.7 1672.35   399.3 1674.28
   405.9 1676.53   412.4 1681.05   422.2 1683.31   461.6 1689.76   487.8 1698.74
     514 1698.15   527.1 1706.97   536.9 1713.93   543.5 1717.24     573  1719.7
#Mann= 11 ,-1 , 0
       0     .12       0     229    .045       0   245.5     .12       0
   258.5     .12       0     265     .06       0   314.1     .08       0
   343.6     .12       0   346.9    .016       0   422.2     .12       0
   487.8    .016       0   527.1     .12       0
Bank Sta=229,245.5
XS Rating Curve= 0 ,0
Exp/Cntr=0.3,0.1

Type RM Length L Ch R = 1 ,584.7   ,139.3,142.1,145.2
XS GIS Cut Line= 3
     2029512.029      143817.391     2029775.267      144115.351
     2029869.668      144268.346
#Sta/Elev= 30
       0 1710.38    32.6 1690.08    65.2 1673.74    91.2 1663.81   114.1 1657.04
   143.4 1651.42   211.8 1648.74   231.4  1646.5   254.2 1646.57   267.2 1644.47
   273.8 1640.42   283.5 1639.13     290 1640.03   292.8 1641.56   312.8 1659.82
   325.9 1668.92   345.4 1671.75     365 1675.72   384.6 1677.85   397.6 1681.14
   407.4 1682.02   410.7 1683.01   420.5 1689.29   423.7 1689.84   446.6 1690.38
   453.2 1689.79   459.7 1692.57   479.3 1704.85   521.8  1717.8   577.4 1733.16
#Mann= 3 ,-1 , 0
       0     .12       0   273.8    .045       0   292.8     .12       0
Bank Sta=273.8,292.8
XS Rating Curve= 0 ,0
Exp/Cntr=0.3,0.1

Type RM Length L Ch R = 1 ,442.6   ,435.6,442.6,483.8
XS GIS Cut Line= 3
     2029418.279      143869.475     2029685.206      144257.495
     2029778.522      144374.683
#Sta/Elev= 30
       0 1736.73    26.2 1724.46   117.7 1671.47     157 1653.68   170.1 1649.35
   179.9 1647.79   235.5 1646.19   251.8  1643.5   271.5 1643.82   274.7 1643.34
  280.471639.939   284.5 1637.84   287.8 1637.59     297 1639.97   310.7 1643.03
   353.2 1655.51   369.6 1661.56   385.9  1668.5   395.7 1676.72   405.6 1680.07
   428.4 1681.19   461.2 1685.37     471 1689.13   480.7 1699.81   500.3 1701.75
   513.3 1709.84   529.6 1714.27   545.9 1720.25     585  1731.1   620.8 1739.54
#Mann= 7 ,-1 , 0
       0     .12       0   251.8    .016       0  280.47    .045       0
     297    .016       0   310.7     .12       0   395.7    .016       0
   461.2     .12       0
Bank Sta=280.47,297
XS Rating Curve= 0 ,0
Exp/Cntr=0.3,0.1

Chan Stop Cuts=-1
Use User Specified Reach Order=0
Composite Channel Slope=5